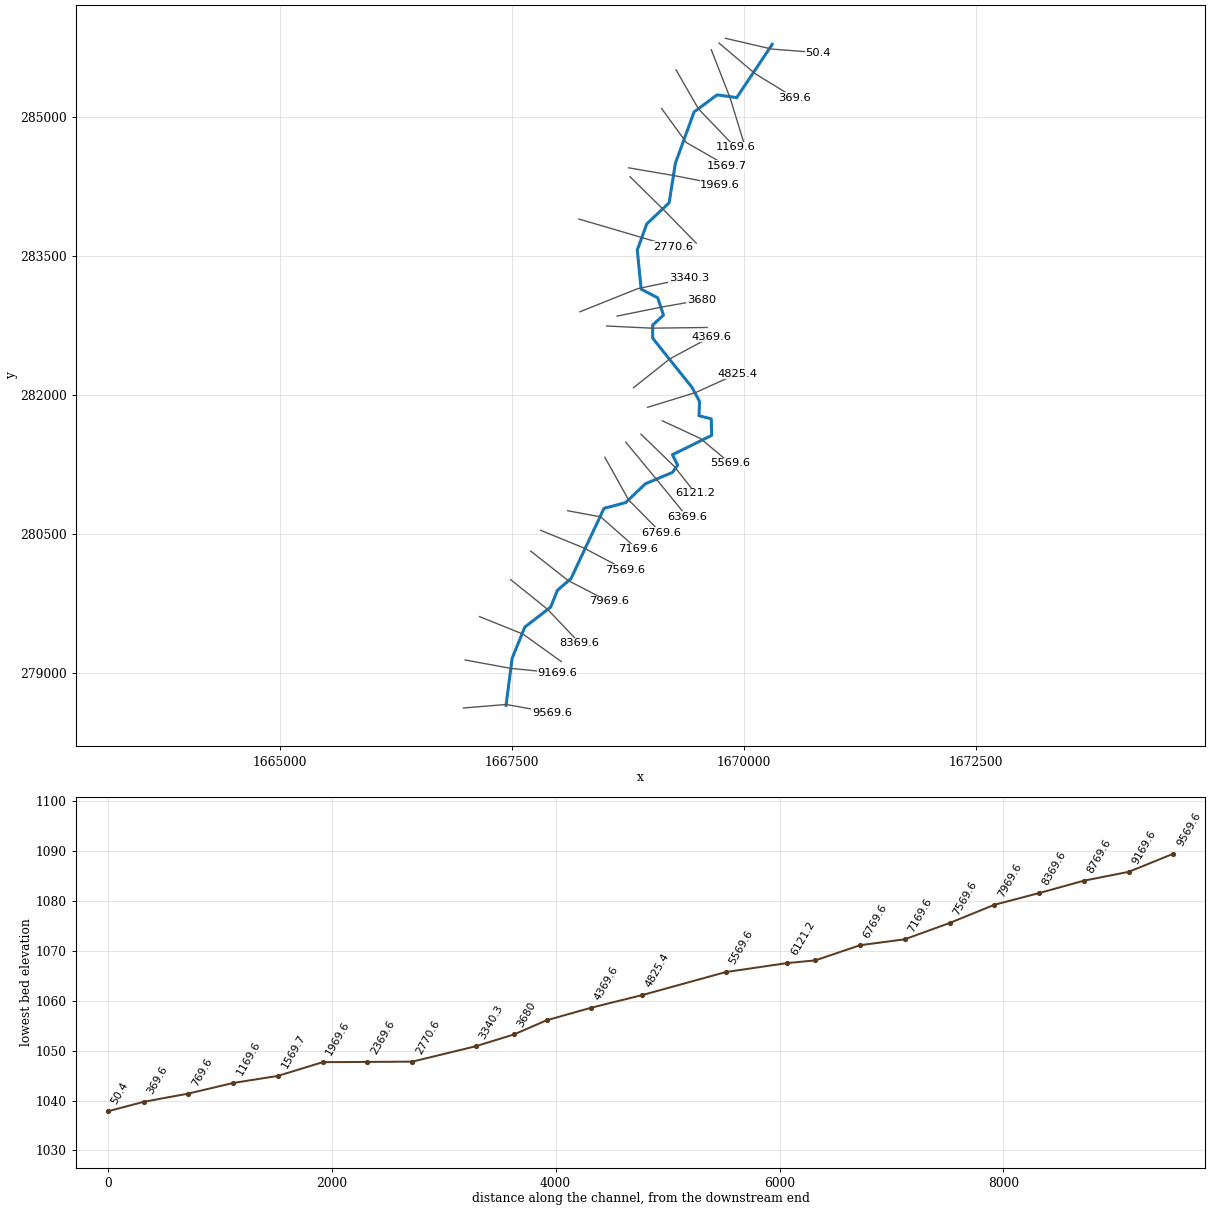
--- PatrsnFk.prj (project) ---

Proj Title=PatrsnFk
Current Plan=p01
Geom File=g01
Flow File=f01
Plan File=p01
DSS Export Rating Curves=0
DSS Export Rating Curve Sorted=0
DSS Export Volume Flow Curves=0
DXF OffsetX=0
DXF OffsetY=0
DXF ScaleX=0
DXF ScaleY=0

--- PatrsnFk.p01 (plan) ---

Plan Title=Floodplain
Program Version=4.00
Geom File=g01
Flow File=f01
K Sum by GR=0
Std Step Tol=0.01
Critical Tol=0.01
Num of Std Step Trials=20
Max Error Tol=0.3
Flow Tol Ratio=0.001
Split Flow NTrial=30
Split Flow Tol=0.02
Split Flow Ratio=0.02
Log Output Level=0
Friction Slope Method=1
Unsteady Friction Slope Method=2
Unsteady Bridges Friction Slope Method=1
Global Log Level=0
CheckData=False
Run HTab=0
Run UNet=0
Run PostProcess=0
UNET Theta=0
UNET Theta Warmup=0
UNET ZTol=0
UNET ZSATol=0
UNET MxIter=0
UNET MaxInSteps=0
UNET DtIC=0
UNET DtMin=0
UNET MaxCRTS=0
UNET WFStab=0
UNET SFStab=0
UNET WFX=0
UNET SFX=0
UNET DSS MLevel=0
UNET DZMax Abort=0
UNET Convert EG Bridges=0
UNET Use Existing IB Tables=0
UNET Froude Limit=0
UNET Froude Power=0
Write IC File=0
Echo Input=False
Echo Output=False
Write Detailed=0

--- PatrsnFk.f01 (steady flow) ---

Flow Title=NFF Regression Equation
Program Version=4.00
Number of Profiles=1
Profile Names=P100yr
River Rch & RM=PatrsnFk,Main      ,9569.6
664.6785
River Rch & RM=PatrsnFk,Main      ,9169.6
669.2061
River Rch & RM=PatrsnFk,Main      ,8769.6
743.2307
River Rch & RM=PatrsnFk,Main      ,7569.6
808.5590
River Rch & RM=PatrsnFk,Main      ,6769.6
885.4690
River Rch & RM=PatrsnFk,Main      ,5569.6
922.2518
River Rch & RM=PatrsnFk,Main      ,3340.3
1020.309
River Rch & RM=PatrsnFk,Main      ,2770.6
1413.859
River Rch & RM=PatrsnFk,Main      ,369.6
1475.262
River Rch & RM=PatrsnFk,Main      ,50.4
1615.486
Boundary for River Rch & Prof#=PatrsnFk,Main      ,1
Up Type=0
Dn Type=3
Dn Slope=0.00372

--- PatrsnFk.g01 (geometry) ---

Geom Title=USGS 3m DEM
Program Version=4.00

River Reach=PatrsnFk     ,Main
Reach XY= 30
     1667434.094      278647.700     1667500.220      279156.555
     1667636.606      279493.192     1667915.481      279708.233
     1667987.962      279889.673     1668134.603      280016.874
     1668490.077      280774.033     1668724.359      280836.990
     1668936.518      281040.031     1669228.117      281162.192
     1669284.522      281240.909     1669227.639      281353.233
     1669650.999      281562.270     1669645.958      281741.310
     1669513.958      281774.191     1669520.435      281927.548
     1669440.517      282078.271     1669014.597      282611.239
     1669015.319      282752.840     1669130.759      282860.119
     1669070.039      283046.120     1668890.517      283140.680
     1668848.659      283562.208     1668951.615      283845.649
     1669192.092      284072.449     1669259.774      284499.368
     1669461.015      285053.098     1669708.935      285237.419
     1669920.857      285207.899     1670303.261      285782.357

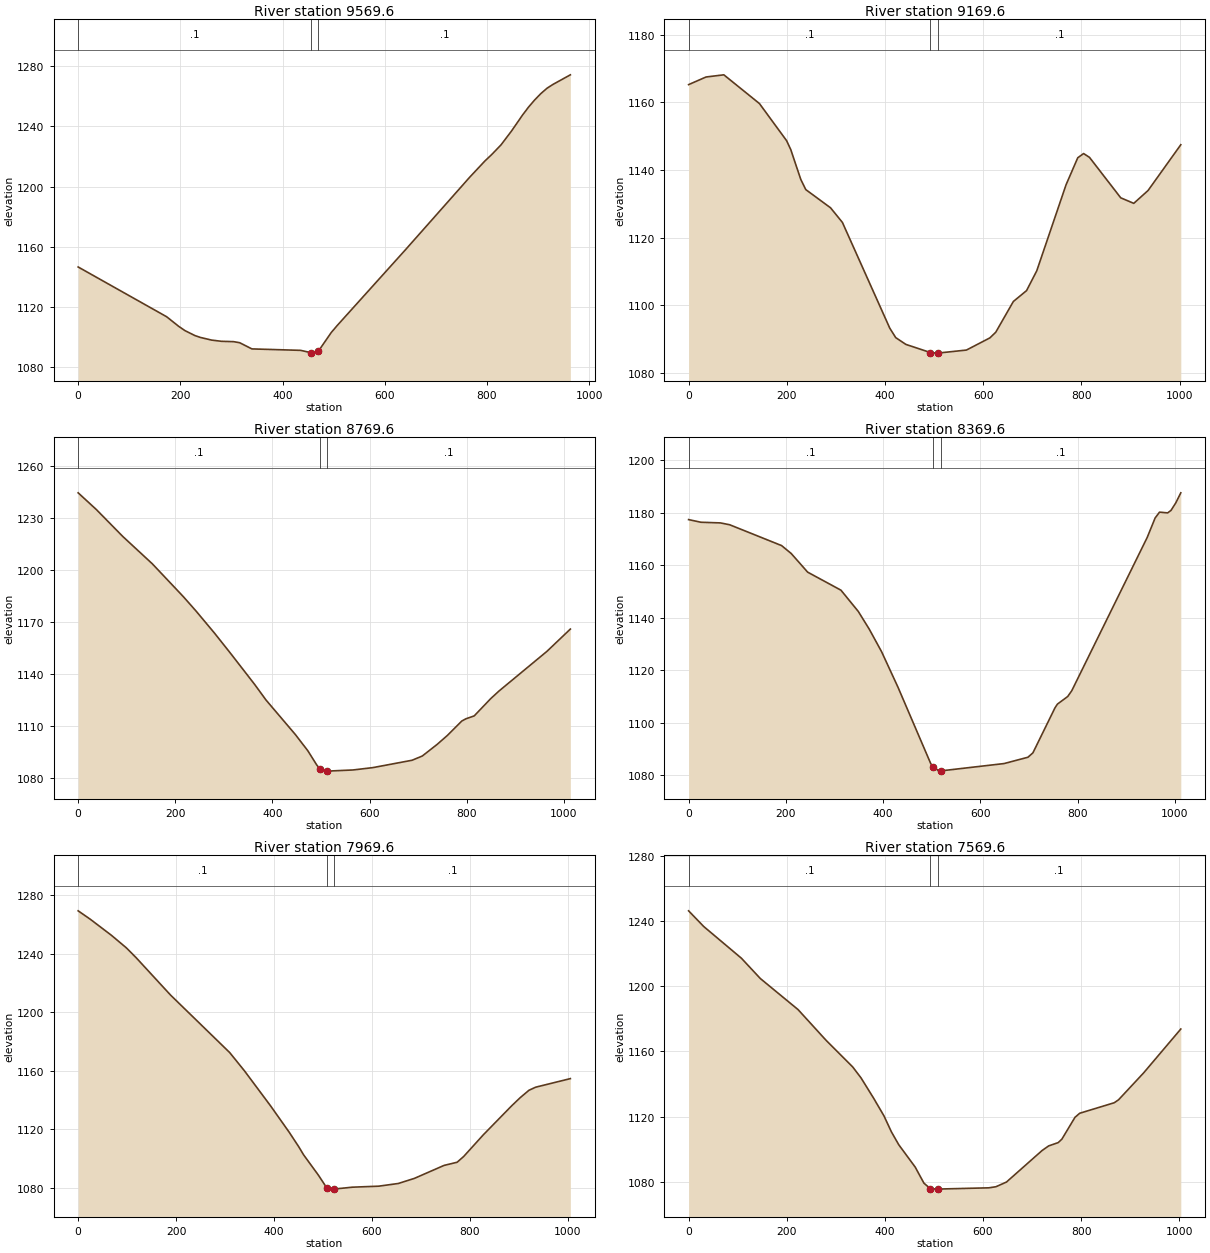
Type RM Length L Ch R = 1 ,9569.6,406.186,400,401.716
XS GIS Cut Line= 3
     1666974.749      278619.262     1667435.879      278657.539
     1667928.341      278568.200
#Sta/Elev= 30
       0 1146.62   173.2 1113.59   197.0 1107.17   208.9 1104.41   228.2 1101.14
   239.2 1099.86   261.2 1098.10   280.4 1097.30   304.2 1097.06   316.1 1096.35
   340.0 1092.25   435.3 1091.29   455.2 1089.79   459.0 1089.45   470.2 1090.79
   495.3 1103.13   507.3 1107.91   640.1 1157.89   766.2 1206.18   796.3 1217.07
   809.0 1221.12   827.5 1227.64   847.9 1236.77   869.3 1247.29   881.4 1252.73
   893.4 1257.47   905.5 1261.69   917.6 1265.25   929.4 1267.81   963.2 1274.13
#Mann= 3 , 0 , 0
       0     0.1       0   455.2   0.045       0   470.2     0.1       0
Bank Sta=   455.2,   470.2
Exp/Cntr=0.3,0.1

Type RM Length L Ch R = 1 ,9169.6,404.478,400,388.173
XS GIS Cut Line= 3
     1666993.580      279137.700     1667485.490      279047.176
     1667985.446      278997.327
#Sta/Elev= 30
       0 1165.28    35.6 1167.54    71.8 1168.18   144.3 1159.68   199.6 1148.70
   208.1 1146.06   228.5 1137.23   238.7 1134.21   289.1 1128.83   313.3 1124.50
   409.8 1093.20   421.9 1090.40   442.6 1088.39   492.7 1085.98   506.4 1085.81
   507.7 1085.82   566.0 1086.72   613.7 1090.32   625.7 1092.00   661.5 1101.09
   688.4 1104.31   709.2 1110.17   768.8 1135.61   792.7 1143.63   804.6 1144.88
   816.6 1143.75   880.3 1131.77   906.8 1130.14   935.9 1133.94  1002.6 1147.49
#Mann= 3 , 0 , 0
       0     0.1       0   492.7   0.045       0   507.7     0.1       0
Bank Sta=   492.7,   507.7
Exp/Cntr=0.3,0.1

Type RM Length L Ch R = 1 ,8769.6,406.906,400,395.41
XS GIS Cut Line= 3
     1667148.215      279605.886     1667616.673      279417.043
     1668029.494      279120.780
#Sta/Elev= 30
       0 1244.38    37.5 1234.74    91.8 1219.26   152.7 1203.48   216.7 1184.51
   242.3 1176.39   280.7 1163.55   314.1 1151.76   363.3 1134.00   386.7 1125.01
   447.1 1105.13   472.7 1095.82   491.0 1087.65   497.6 1085.31   500.1 1084.76
   511.9 1084.04   512.6 1084.04   565.9 1084.71   606.6 1086.06   687.3 1090.30
   708.4 1092.74   738.7 1099.38   760.4 1104.69   789.6 1112.88   798.2 1114.20
   815.2 1115.84   849.3 1125.82   866.3 1130.19   965.0 1153.05  1013.2 1165.89
#Mann= 3 , 0 , 0
       0     0.1       0   497.6   0.045       0   512.6     0.1       0
Bank Sta=   497.6,   512.6
Exp/Cntr=0.3,0.1

Type RM Length L Ch R = 1 ,8369.6,399.285,400,408.9
XS GIS Cut Line= 3
     1667485.164      280004.457     1667882.880      279683.525
     1668227.654      279319.511
#Sta/Elev= 30
       0 1177.38    25.4 1176.37    65.5 1176.12    84.6 1175.41   191.4 1167.47
   211.1 1164.46   244.9 1157.36   313.4 1150.49   349.1 1142.38   371.6 1135.64
   396.9 1127.08   430.7 1113.52   498.2 1084.37   503.6 1083.21   515.1 1081.56
   518.6 1081.65   648.9 1084.44   698.0 1086.85   708.2 1088.51   753.6 1105.67
   758.6 1107.08   779.8 1109.99   788.1 1112.18   943.3 1170.58   959.6 1178.00
   968.6 1180.22   985.4 1179.94   992.3 1180.90  1002.2 1183.79  1012.4 1187.58
#Mann= 3 , 0 , 0
       0     0.1       0   503.6   0.045       0   518.6     0.1       0
Bank Sta=   503.6,   518.6
Exp/Cntr=0.3,0.1

Type RM Length L Ch R = 1 ,7969.6,394.326,400,398.43
XS GIS Cut Line= 3
     1667699.430      280313.017     1668104.827      279994.214
     1668540.190      279769.841
#Sta/Elev= 30
       0 1269.18    24.9 1263.41    67.9 1252.49    98.2 1243.99   118.0 1237.36
   188.8 1211.67   309.6 1172.42   339.8 1159.93   392.8 1136.17   430.8 1118.21
   450.4 1108.26   460.6 1102.60   490.9 1088.70   506.9 1080.57   508.2 1080.29
   515.3 1079.21   523.2 1079.28   560.5 1080.54   613.9 1081.22   654.0 1083.06
   686.8 1086.53   747.5 1095.40   774.2 1097.56   787.6 1101.50   827.6 1116.25
   885.5 1136.05   903.1 1141.66   920.8 1146.66   934.5 1148.78  1005.5 1154.65
#Mann= 3 , 0 , 0
       0     0.1       0   508.2   0.045       0   523.2     0.1       0
Bank Sta=   508.2,   523.2
Exp/Cntr=0.3,0.1

Type RM Length L Ch R = 1 ,7569.6,395.74,400,392.887
XS GIS Cut Line= 3
     1667807.445      280537.077     1668270.401      280348.098
     1668715.175      280112.963
#Sta/Elev= 30
       0 1246.15    30.8 1236.55   107.7 1217.08   146.2 1204.65   223.1 1185.61
   279.8 1166.91   334.4 1150.48   351.4 1143.75   377.0 1131.34   398.2 1120.44
   413.4 1110.63   428.3 1102.77   461.9 1089.04   479.6 1079.22   492.5 1075.90
   505.5 1075.56   507.5 1075.59   612.0 1076.36   626.4 1077.03   647.8 1079.90
   720.4 1099.22   733.8 1102.05   753.2 1104.07   760.7 1106.17   787.5 1119.59
   797.1 1122.07   867.4 1128.50   876.2 1130.30   927.4 1146.83  1003.1 1173.70
#Mann= 3 , 0 , 0
       0     0.1       0   492.5   0.045       0   507.5     0.1       0
Bank Sta=   492.5,   507.5
Exp/Cntr=0.3,0.1

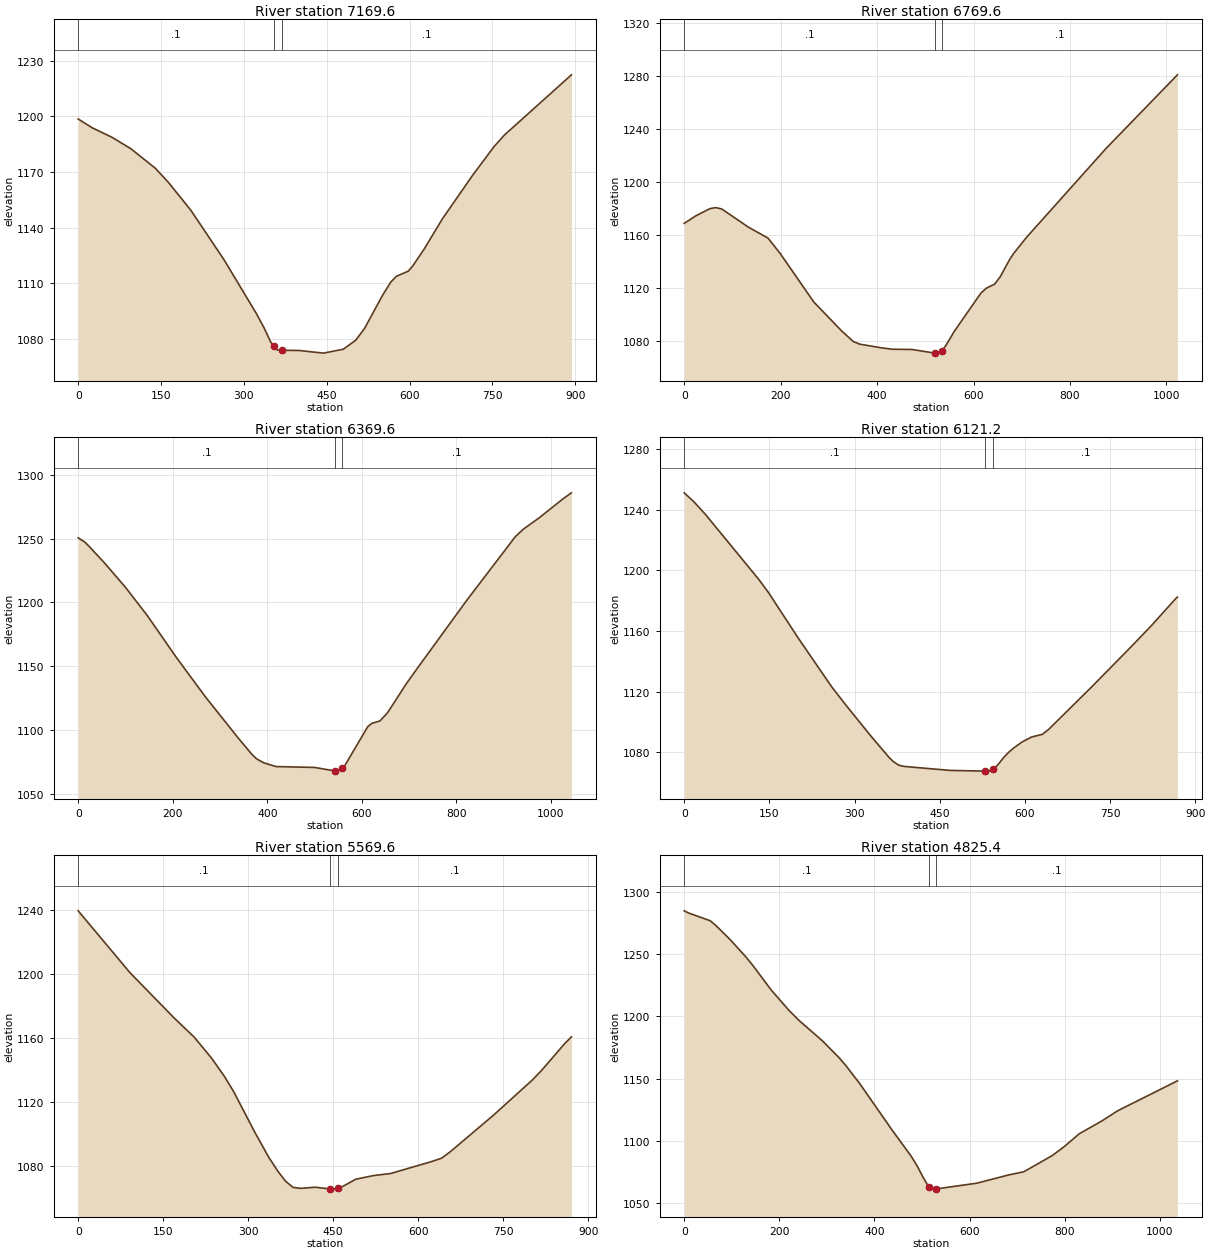
Type RM Length L Ch R = 1 ,7169.6,420.475,400,399.224
XS GIS Cut Line= 3
     1668098.760      280748.753     1668454.458      280682.618
     1668853.275      280331.299
#Sta/Elev= 30
       0 1198.64    25.4 1193.88    61.3 1188.76    95.0 1182.68   139.8 1172.04
   163.1 1164.52   203.7 1149.51   264.0 1122.73   322.1 1093.92   336.5 1085.99
   348.6 1078.27   354.3 1076.29   360.6 1073.96   369.3 1073.81   399.5 1073.75
   444.1 1072.30   480.0 1074.40   502.7 1079.33   518.5 1085.62   551.0 1103.46
   566.0 1110.64   576.2 1113.75   597.6 1116.53   605.8 1119.35   626.7 1128.57
   659.6 1144.83   713.5 1167.98   752.8 1183.68   771.7 1189.97   893.1 1222.48
#Mann= 3 , 0 , 0
       0     0.1       0   354.3   0.045       0   369.3     0.1       0
Bank Sta=   354.3,   369.3
Exp/Cntr=0.3,0.1

Type RM Length L Ch R = 1 ,6769.6,396.124,400,397.3
XS GIS Cut Line= 3
     1668498.857      281326.001     1668755.341      280865.611
     1669102.942      280512.040
#Sta/Elev= 30
       0 1168.84    24.1 1174.53    52.8 1179.87    64.9 1180.76    78.0 1179.69
   132.8 1166.09   174.0 1157.70   199.2 1146.09   268.7 1109.65   325.5 1088.21
   350.3 1079.91   363.9 1077.88   409.7 1075.06   431.8 1074.03   472.6 1073.86
   519.5 1071.12   527.0 1071.11   531.7 1071.57   534.5 1072.79   543.6 1077.39
   560.2 1087.59   615.6 1116.49   626.8 1120.07   643.5 1123.02   655.1 1128.47
   674.4 1141.34   682.8 1146.03   710.1 1158.42   875.2 1225.46  1022.8 1280.75
#Mann= 3 , 0 , 0
       0     0.1       0   519.5   0.045       0   534.5     0.1       0
Bank Sta=   519.5,   534.5
Exp/Cntr=0.3,0.1

Type RM Length L Ch R = 1 ,6369.6,248.674,248.419,248.657
XS GIS Cut Line= 3
     1668724.949      281488.801     1669076.009      281063.703
     1669386.659      280682.386
#Sta/Elev= 30
       0 1250.54    13.6 1247.41    22.9 1243.97    53.7 1231.74    99.9 1211.91
   146.1 1189.81   207.6 1157.03   269.2 1126.12   337.9 1094.23   367.8 1081.02
   377.0 1077.80   392.4 1074.58   418.4 1071.64   500.2 1070.94   543.8 1068.15
   544.9 1068.07   558.8 1070.45   561.7 1071.00   612.4 1102.86   620.8 1105.40
   638.3 1107.33   654.6 1113.91   693.3 1136.06   712.1 1145.88   823.3 1202.42
   924.6 1251.54   941.5 1257.37   975.0 1266.23  1025.9 1281.24  1043.2 1285.80
#Mann= 3 , 0 , 0
       0     0.1       0   543.8   0.045       0   558.8     0.1       0
Bank Sta=   543.8,   558.8
Exp/Cntr=0.3,0.1

Type RM Length L Ch R = 1 ,6121.2,541.102,551.581,554.091
XS GIS Cut Line= 3
     1668889.003      281574.732     1669246.673      281228.255
     1669476.185      280936.769
#Sta/Elev= 30
       0 1251.17    17.0 1245.31    38.1 1236.63   131.8 1193.83   148.8 1185.20
   200.0 1155.82   260.5 1122.80   286.0 1110.55   327.7 1091.22   361.3 1076.36
   368.7 1073.75   378.1 1071.45   387.7 1070.63   467.9 1068.03   529.4 1067.54
   537.9 1067.62   544.4 1069.00   551.5 1071.29   563.2 1076.73   571.7 1080.01
   580.1 1082.72   594.7 1086.67   611.9 1090.06   630.9 1091.81   642.1 1095.12
   717.7 1123.10   789.3 1150.40   823.5 1163.77   866.0 1181.48   868.8 1182.34
#Mann= 3 , 0 , 0
       0     0.1       0   529.4   0.045       0   544.4     0.1       0
Bank Sta=   529.4,   544.4
Exp/Cntr=0.3,0.1

Type RM Length L Ch R = 1 ,5569.6,725.53,744.165,765.521
XS GIS Cut Line= 3
     1669118.545      281719.490     1669528.177      281529.631
     1669850.174      281261.711
#Sta/Elev= 30
       0 1239.71    91.2 1201.12   169.7 1172.58   204.6 1160.80   235.2 1147.68
   258.3 1136.07   274.4 1126.66   311.9 1101.14   336.4 1085.56   352.9 1076.67
   366.0 1070.67   379.1 1066.82   392.4 1066.21   418.4 1066.92     444 1065.86
   449.3 1065.73     459 1066.36   468.6 1067.75   489.6 1071.90   520.5 1074.17
   551.4 1075.50   623.4 1082.94   640.3 1084.93   644.1 1085.80   657.1 1089.24
   733.0 1111.99   800.4 1133.61   817.3 1139.78   858.5 1156.71   870.4 1160.90
#Mann= 3 , 0 , 0
       0     0.1       0     444   0.045       0     459     0.1       0
Bank Sta=     444,     459
Exp/Cntr=0.3,0.1

Type RM Length L Ch R = 1 ,4825.4,447.289,455.835,460.314
XS GIS Cut Line= 3
     1668959.315      281864.596     1669479.238      282024.978
     1669928.455      282228.515
#Sta/Elev= 30
       0 1284.90     9.3 1283.15    54.4 1276.98    66.9 1273.00    97.3 1261.51
   129.0 1248.14   144.8 1240.77   182.7 1221.35   220.7 1204.70   240.8 1196.97
   290.5 1180.41   325.2 1166.99   340.2 1160.30   368.7 1146.17   437.5 1108.42
   476.9 1087.76   489.3 1080.17   501.7 1071.06   513.8 1063.04   526.6 1061.13
   528.8 1061.24   615.4 1065.92   682.1 1072.52   714.0 1075.09   773.4 1088.01
   799.4 1095.41   830.6 1105.65   877.6 1115.84   911.4 1124.13  1037.0 1148.19
#Mann= 3 , 0 , 0
       0     0.1       0   513.8   0.045       0   528.8     0.1       0
Bank Sta=   513.8,   528.8
Exp/Cntr=0.3,0.1

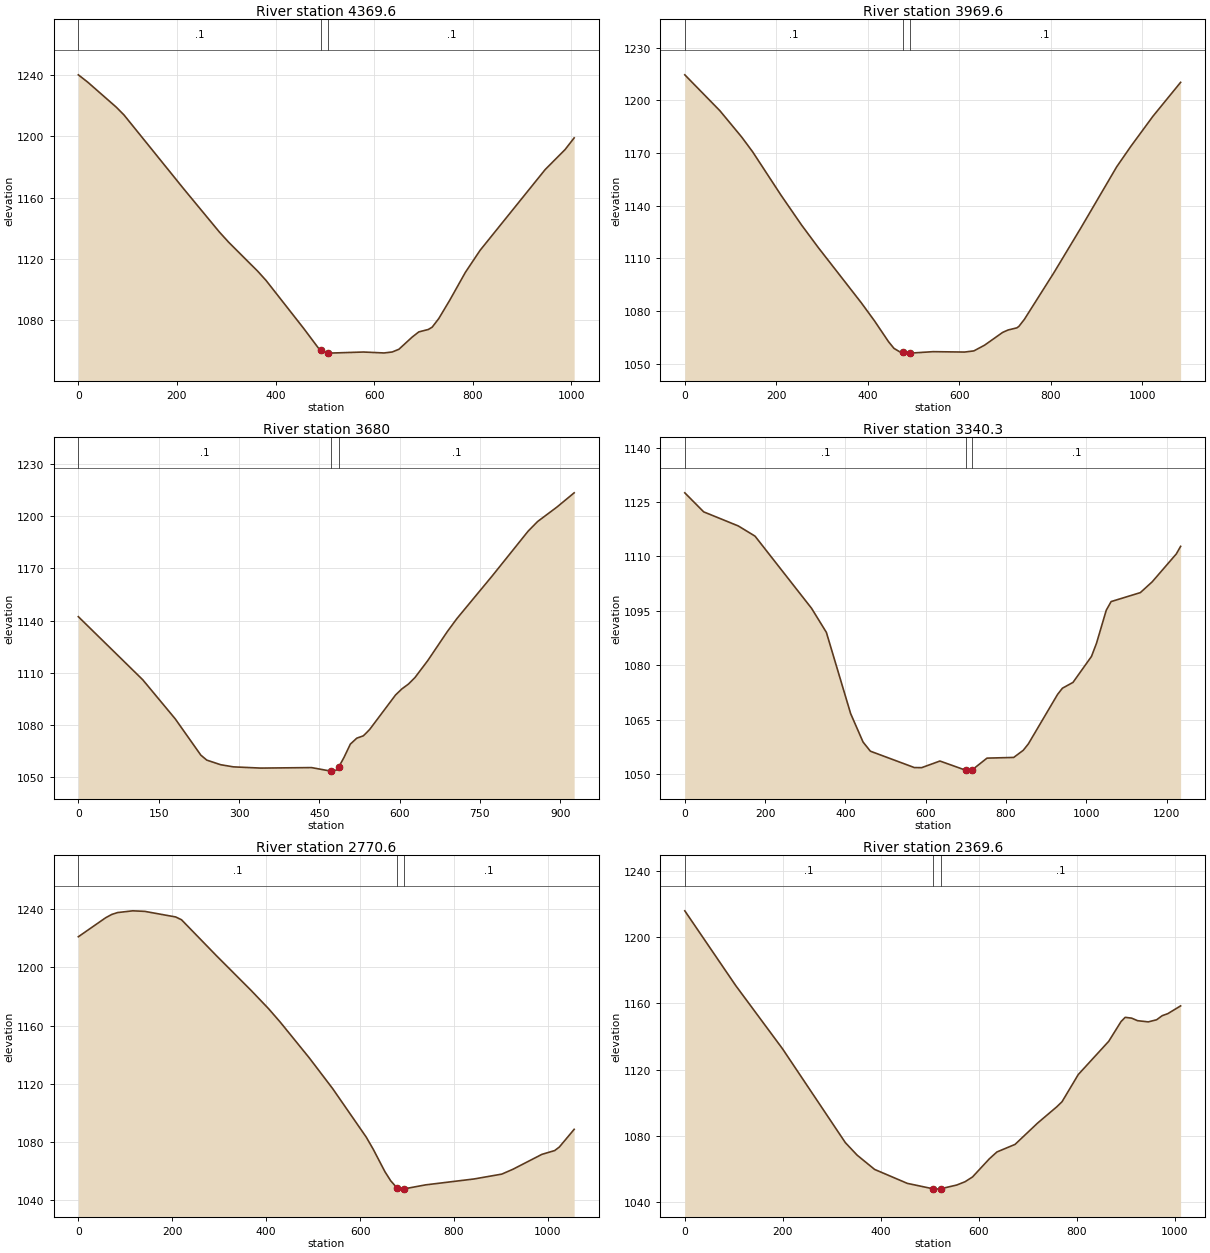
Type RM Length L Ch R = 1 ,4369.6,416.441,400,389.296
XS GIS Cut Line= 3
     1668808.275      282076.719     1669199.284      282387.691
     1669644.878      282627.392
#Sta/Elev= 30
       0 1239.99    19.0 1235.23    76.9 1218.93    92.6 1213.84   213.9 1165.60
   286.0 1137.56   305.0 1130.85   364.2 1111.87   380.8 1105.95   456.7 1074.85
   487.0 1061.86   492.1 1060.48   495.9 1059.45   507.1 1058.62   508.1 1058.60
   578.3 1059.32   620.0 1058.71   636.7 1059.35   650.2 1061.12   677.1 1069.07
   690.6 1072.44   709.7 1074.01   717.6 1075.51   731.1 1081.16   753.6 1093.27
   785.0 1111.26   814.9 1125.64   946.8 1178.23   987.2 1191.28  1005.6 1198.89
#Mann= 3 , 0 , 0
       0     0.1       0   492.1   0.045       0   507.1     0.1       0
Bank Sta=   492.1,   507.1
Exp/Cntr=0.3,0.1

Type RM Length L Ch R = 1 ,3969.6,283.791,289.64,293.319
XS GIS Cut Line= 3
     1668518.952      282742.756     1669002.821      282719.418
     1669602.369      282726.665
#Sta/Elev= 30
       0 1214.48    76.9 1194.00   124.5 1179.02   148.3 1170.67   210.6 1145.87
   255.2 1129.02   291.9 1116.14   386.0 1084.68   414.7 1074.44   445.4 1062.59
   457.3 1058.78   469.2 1056.93   476.9 1056.46   491.9 1056.09   493.0 1056.07
   542.8 1056.90   611.7 1056.68   632.0 1057.34   655.5 1060.61   694.8 1067.85
   706.7 1069.23   725.9 1070.45   730.4 1071.28   742.3 1075.25   807.2 1101.95
   866.7 1127.68   944.1 1162.07   975.4 1173.85  1023.5 1190.90  1084.0 1210.21
#Mann= 3 , 0 , 0
       0     0.1       0   476.9   0.045       0   491.9     0.1       0
Bank Sta=   476.9,   491.9
Exp/Cntr=0.3,0.1

Type RM Length L Ch R = 1 ,3680,337.051,339.699,341.147
XS GIS Cut Line= 3
     1668632.154      282849.632     1669097.712      282944.422
     1669541.582      283023.343
#Sta/Elev= 30
       0 1142.22   120.4 1105.84   181.0 1083.34   228.8 1062.45   239.9 1059.59
   265.8 1056.94   289.7 1055.70   340.6 1055.00   435.4 1055.29   471.5 1053.25
   481.6 1053.81   486.5 1055.74   495.9 1061.02   508.0 1068.82   520.0 1072.24
   532.1 1073.56   537.0 1075.02   544.1 1077.28   592.4 1097.12   604.4 1100.67
   616.5 1103.40   628.6 1107.14   652.7 1117.00   688.9 1133.56   707.0 1141.14
   773.3 1165.85   840.0 1191.50   857.7 1197.04   893.9 1205.39   925.9 1213.56
#Mann= 3 , 0 , 0
       0     0.1       0   471.5   0.045       0   486.5     0.1       0
Bank Sta=   471.5,   486.5
Exp/Cntr=0.3,0.1

Type RM Length L Ch R = 1 ,3340.3,580.736,569.696,558.656
XS GIS Cut Line= 3
     1668231.598      282896.637     1668853.903      283145.980
     1669406.315      283261.539
#Sta/Elev= 30
       0 1127.53    47.0 1122.29   133.4 1118.40   174.9 1115.60   315.6 1095.74
   352.6 1089.10   413.0 1066.74   443.9 1058.91   462.2 1056.38   571.7 1051.87
   590.0 1051.85   635.4 1053.67   700.3 1051.11   709.9 1050.89   715.3 1051.20
   752.6 1054.47   819.1 1054.66   842.9 1056.63   855.5 1058.37   928.3 1072.01
   940.4 1073.72   966.8 1075.33  1012.8 1082.48  1025.3 1086.10  1049.6 1095.20
  1061.7 1097.58  1134.5 1100.05  1163.9 1103.01  1224.1 1110.71  1234.8 1112.79
#Mann= 3 , 0 , 0
       0     0.1       0   700.3   0.045       0   715.3     0.1       0
Bank Sta=   700.3,   715.3
Exp/Cntr=0.3,0.1

Type RM Length L Ch R = 1 ,2770.6,411.724,400.964,389.727
XS GIS Cut Line= 3
     1668218.821      283897.409     1668687.721      283759.711
     1669231.518      283598.959
#Sta/Elev= 30
       0 1220.95    58.4 1234.03    71.2 1236.26    83.5 1237.54   115.8 1238.74
   141.4 1238.37   207.3 1234.53   219.7 1232.61   293.9 1208.01   368.1 1184.07
   405.3 1171.52   430.0 1162.36   491.9 1137.79   541.4 1116.83   613.1 1083.46
   628.1 1075.08   652.8 1059.79   665.2 1053.50   677.6 1049.01   679.1 1048.86
   690.0 1047.79   694.1 1047.99   739.5 1050.71   842.4 1054.75   901.7 1058.09
   925.2 1061.38   987.1 1071.64  1014.4 1074.26  1024.3 1076.69  1055.8 1088.82
#Mann= 3 , 0 , 0
       0     0.1       0   679.1   0.045       0   694.1     0.1       0
Bank Sta=   679.1,   694.1
Exp/Cntr=0.3,0.1

Type RM Length L Ch R = 1 ,2369.6,386.348,400,413.606
XS GIS Cut Line= 3
     1668771.123      284353.764     1669137.445      283992.628
     1669484.869      283636.957
#Sta/Elev= 30
       0 1215.89   103.9 1170.73   199.4 1132.52   327.6 1075.81   351.6 1068.26
   387.3 1059.63   454.0 1051.21   506.9 1047.90   512.3 1047.73   521.9 1047.94
   554.8 1050.20   571.8 1052.20   587.0 1055.08   621.5 1066.09   636.8 1070.18
   673.8 1074.76   719.8 1087.64   758.7 1097.41   769.6 1100.52   802.8 1116.97
   865.0 1137.08   890.1 1149.00   898.5 1151.53   911.6 1151.05   923.7 1149.51
   945.6 1148.79   962.6 1150.06   974.1 1152.55   985.3 1153.73  1011.6 1158.45
#Mann= 3 , 0 , 0
       0     0.1       0   506.9   0.045       0   521.9     0.1       0
Bank Sta=   506.9,   521.9
Exp/Cntr=0.3,0.1

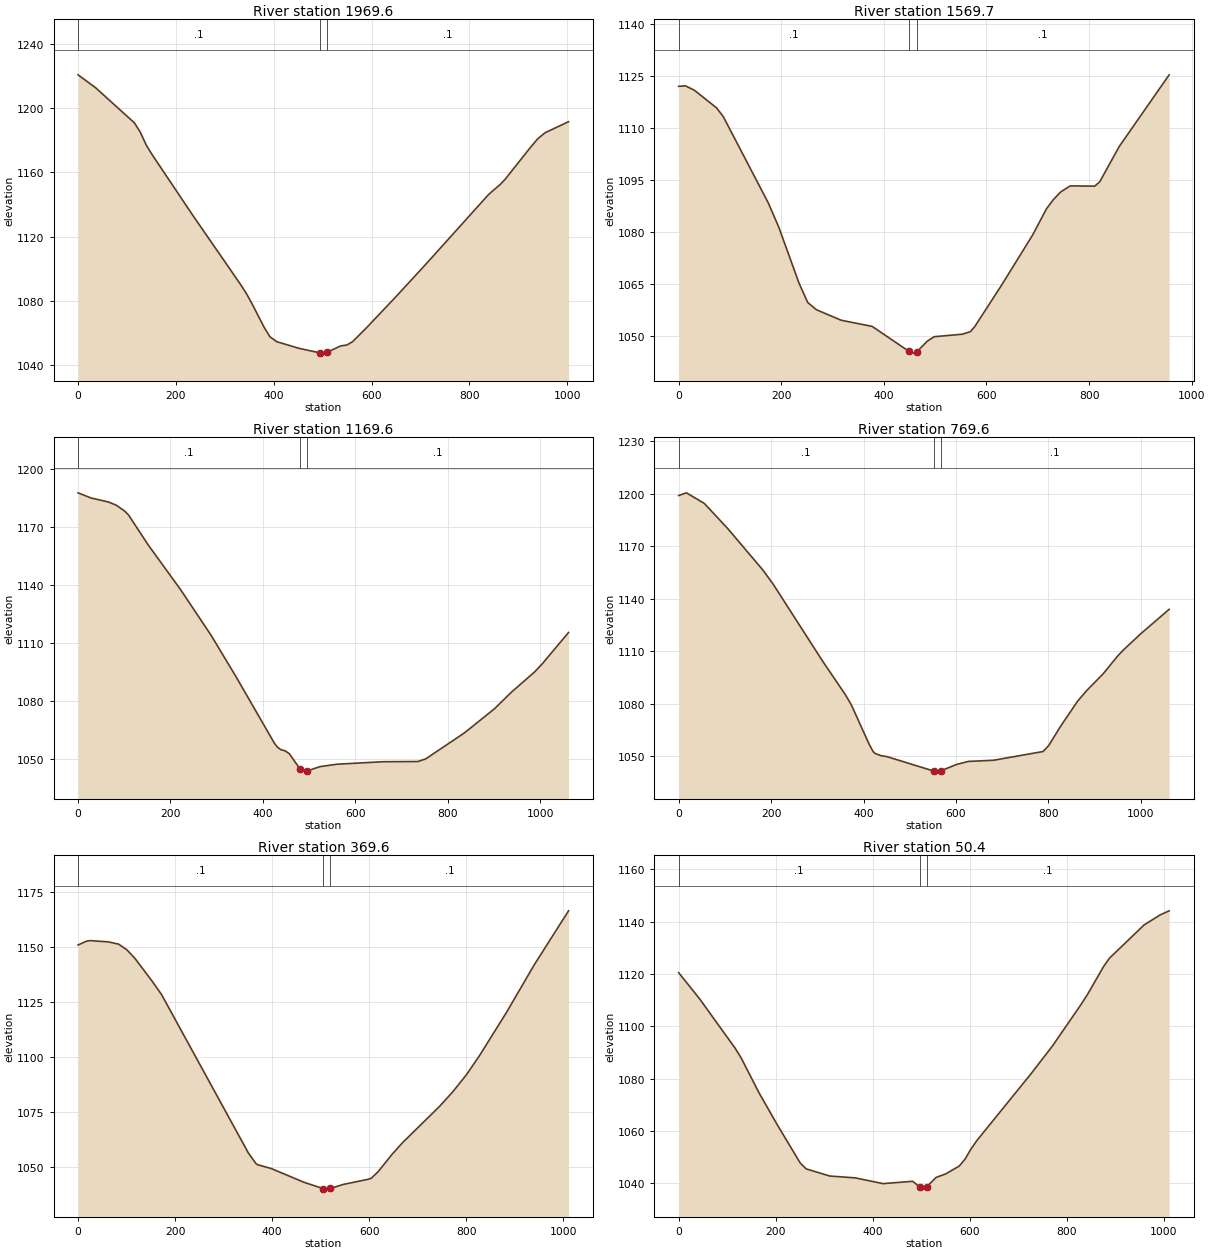
Type RM Length L Ch R = 1 ,1969.6,419.502,399.948,390.887
XS GIS Cut Line= 3
     1668755.367      284450.210     1669249.862      284365.534
     1669741.391      284269.577
#Sta/Elev= 30
       0 1220.72    35.7 1212.73   115.2 1190.84   127.2 1185.08   139.2 1177.15
   151.3 1171.13   235.6 1132.88   332.0 1090.45   344.3 1084.61   356.1 1078.08
   380.2 1063.79   392.2 1057.86   406.0 1054.81   452.4 1050.60   494.2 1047.86
   500.6 1047.68   509.2 1048.26   536.9 1052.18   549.2 1052.71   561.1 1054.81
   589.7 1063.50   650.4 1083.00   711.1 1103.06   839.3 1146.38   863.5 1152.76
   873.1 1155.84   924.0 1175.37   939.5 1180.96   954.5 1184.71  1002.5 1191.58
#Mann= 3 , 0 , 0
       0     0.1       0   494.2   0.045       0   509.2     0.1       0
Bank Sta=   494.2,   509.2
Exp/Cntr=0.3,0.1

Type RM Length L Ch R = 1 ,1569.7,401.969,400.052,393.475
XS GIS Cut Line= 3
     1669110.370      285091.524     1669377.719      284723.058
     1669812.305      284474.102
#Sta/Elev= 30
       0 1122.07    13.3 1122.21    30.5 1120.96    74.0 1115.83    87.0 1113.31
   175.0 1088.28   195.3 1081.30   234.5 1065.23   251.5 1059.59   268.5 1057.48
   316.6 1054.45   377.2 1052.66   449.1 1045.43   457.2 1044.93   464.1 1045.27
   484.5 1048.37   498.2 1049.68   552.9 1050.40   568.7 1051.15   577.4 1052.65
   629.6 1064.61   689.8 1079.03   717.1 1086.69   730.8 1089.38   744.5 1091.52
   763.3 1093.29   811.1 1093.21   820.9 1094.49   858.8 1104.67   956.1 1125.40
#Mann= 3 , 0 , 0
       0     0.1       0   449.1   0.045       0   464.1     0.1       0
Bank Sta=   449.1,   464.1
Exp/Cntr=0.3,0.1

Type RM Length L Ch R = 1 ,1169.6,401.354,400,390.119
XS GIS Cut Line= 3
     1669266.236      285508.305     1669509.018      285085.442
     1669906.173      284671.375
#Sta/Elev= 30
       0 1187.46    27.9 1184.81    65.8 1182.72    82.6 1181.06   100.6 1178.08
   109.3 1175.99   151.1 1160.74   222.4 1137.20   288.0 1113.73   342.8 1091.94
   424.9 1057.93   431.1 1055.97   438.6 1054.63   448.5 1053.96   457.2 1052.50
   480.1 1044.68   483.3 1043.99   494.5 1043.51   495.1 1043.56   523.3 1045.83
   560.3 1047.09   660.5 1048.37   735.3 1048.48   752.1 1049.82   836.1 1063.30
   900.6 1075.69   938.7 1084.57   987.2 1094.68  1003.6 1098.80  1061.3 1115.22
#Mann= 3 , 0 , 0
       0     0.1       0   480.1   0.045       0   495.1     0.1       0
Bank Sta=   480.1,   495.1
Exp/Cntr=0.3,0.1

Type RM Length L Ch R = 1 ,769.6,390.72,400,415.658
XS GIS Cut Line= 3
     1669646.400      285725.495     1669849.523      285204.184
     1669996.834      284724.610
#Sta/Elev= 30
       0 1198.91    16.7 1200.47    55.2 1194.48   106.1 1180.06   182.6 1156.21
   205.0 1148.05   311.0 1104.43   361.0 1084.95   373.7 1079.17   411.9 1056.87
   420.3 1052.73   424.7 1051.52   437.4 1050.24   450.2 1049.71     552 1041.41
   559.5 1041.39     567 1041.58   602.0 1045.27   626.8 1046.94   681.3 1047.61
   788.3 1052.60   800.7 1056.10   825.5 1066.73   862.8 1081.32   882.5 1087.39
   918.4 1097.07   949.7 1107.21   962.2 1110.67   999.4 1119.87  1061.0 1133.88
#Mann= 3 , 0 , 0
       0     0.1       0     552   0.045       0     567     0.1       0
Bank Sta=     552,     567
Exp/Cntr=0.3,0.1

Type RM Length L Ch R = 1 ,369.6,308.318,319.194,328.943
XS GIS Cut Line= 3
     1669729.033      285797.302     1670119.766      285465.982
     1670544.393      285204.997
#Sta/Elev= 30
       0 1150.81    16.2 1152.45    24.1 1152.82    62.0 1152.24    83.6 1151.20
   100.5 1148.64   117.1 1144.76   153.8 1134.01   172.2 1128.20   351.0 1056.15
   366.6 1051.36   370.0 1050.83   397.7 1049.13   465.9 1042.81   504.8    1040
   512.3 1039.73   519.8 1040.02   545.7 1041.83   599.6 1044.29   604.8 1044.79
   618.8 1047.79   646.6 1055.45   668.6 1060.86   744.2 1077.23   772.1 1084.00
   799.9 1091.68   827.8 1100.67   883.6 1120.43   939.3 1141.54  1010.7 1166.36
#Mann= 3 , 0 , 0
       0     0.1       0   504.8   0.045       0   519.8     0.1       0
Bank Sta=   504.8,   519.8
Exp/Cntr=0.3,0.1

Type RM Length L Ch R = 1 ,50.4,48.973,50.421,49.545
XS GIS Cut Line= 3
     1669800.215      285848.104     1670299.153      285731.887
     1670796.108      285693.721
#Sta/Elev= 30
       0 1120.50    43.3 1110.48   116.5 1091.63   128.7 1087.98   165.2 1074.76
   201.8 1062.86   250.6 1047.80   262.8 1045.57   311.5 1042.84   363.9 1042.14
   421.2 1039.94   482.2 1040.83   496.3 1038.73   506.6 1037.84   511.3 1038.75
   530.5 1042.31   549.9 1043.62   578.2 1046.65   590.1 1049.28   602.0 1053.04
   613.9 1056.24   726.8 1082.06   771.1 1092.71   830.4 1108.69   843.3 1112.44
   875.8 1122.90   887.8 1126.04   959.2 1138.74   992.2 1142.55  1010.7 1144.11
#Mann= 3 , 0 , 0
       0     0.1       0   496.3   0.045       0   511.3     0.1       0
Bank Sta=   496.3,   511.3
Exp/Cntr=0.3,0.1